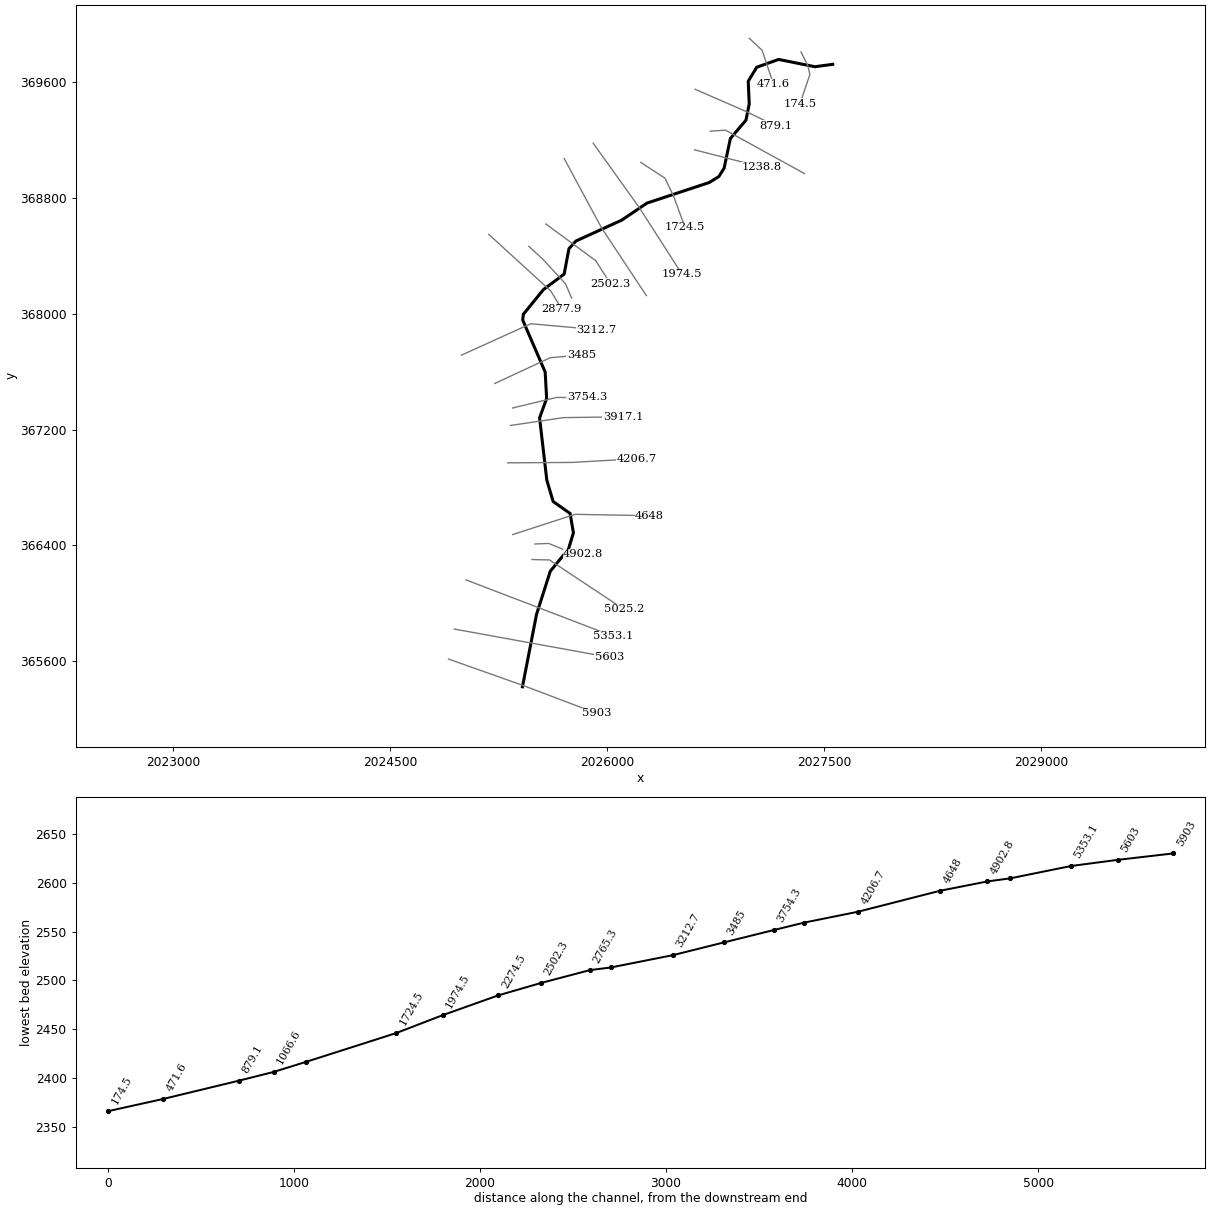
--- SurbaughCk.prj (project) ---

Proj Title=SurbaughCk
Current Plan=p01
Geom File=g01
Flow File=f01
Plan File=p01
DSS Export Rating Curves=0
DSS Export Rating Curve Sorted=0
DSS Export Volume Flow Curves=0
DXF OffsetX=0
DXF OffsetY=0
DXF ScaleX=0
DXF ScaleY=0

--- SurbaughCk.p01 (plan) ---

Plan Title=Floodplain
Program Version=4.00
Geom File=g01
Flow File=f01
K Sum by GR=0
Std Step Tol=0.01
Critical Tol=0.01
Num of Std Step Trials=20
Max Error Tol=0.3
Flow Tol Ratio=0.001
Split Flow NTrial=30
Split Flow Tol=0.02
Split Flow Ratio=0.02
Log Output Level=0
Friction Slope Method=1
Unsteady Friction Slope Method=2
Unsteady Bridges Friction Slope Method=1
Global Log Level=0
CheckData=False
Run HTab=0
Run UNet=0
Run PostProcess=0
UNET Theta=0
UNET Theta Warmup=0
UNET ZTol=0
UNET ZSATol=0
UNET MxIter=0
UNET MaxInSteps=0
UNET DtIC=0
UNET DtMin=0
UNET MaxCRTS=0
UNET WFStab=0
UNET SFStab=0
UNET WFX=0
UNET SFX=0
UNET DSS MLevel=0
UNET DZMax Abort=0
UNET Convert EG Bridges=0
UNET Use Existing IB Tables=0
UNET Froude Limit=0
UNET Froude Power=0
Write IC File=0
Echo Input=False
Echo Output=False
Write Detailed=0

--- SurbaughCk.f01 (steady flow) ---

Flow Title=NFF Regression Equation
Program Version=4.00
Number of Profiles=1
Profile Names=P100yr
River Rch & RM=SurbaughCk,Main      ,5903
518.2857
River Rch & RM=SurbaughCk,Main      ,3212.7
555.6613
River Rch & RM=SurbaughCk,Main      ,2877.9
693.8575
River Rch & RM=SurbaughCk,Main      ,174.5
743.6366
Boundary for River Rch & Prof#=SurbaughCk,Main      ,1
Up Type=0
Dn Type=3
Dn Slope=0.045364

--- SurbaughCk.g01 (geometry) ---

Geom Title=USGS 3m DEM
Program Version=4.00

River Reach=SurbaughCk     ,Main
Reach XY= 30
     2025414.857      365422.403     2025512.079      365922.403
     2025607.361      366221.372     2025733.037      366374.713
     2025767.288      366486.639     2025744.329      366620.527
     2025627.119      366703.084     2025583.292      366850.871
     2025533.350      367280.982     2025582.086      367415.846
     2025571.842      367598.501     2025416.593      367957.704
     2025421.300      367997.861     2025560.691      368168.931
     2025703.052      368274.833     2025736.195      368450.665
     2025784.649      368504.000     2026100.929      368648.229
     2026275.968      368766.153     2026706.524      368908.514
     2026772.689      368949.731     2026808.954      369007.472
     2026852.316      369212.876     2026959.996      369339.070
     2026982.566      369451.917     2026975.621      369608.233
     2027034.649      369705.389     2027185.691      369759.208
     2027436.558      369708.861     2027559.705      369725.315

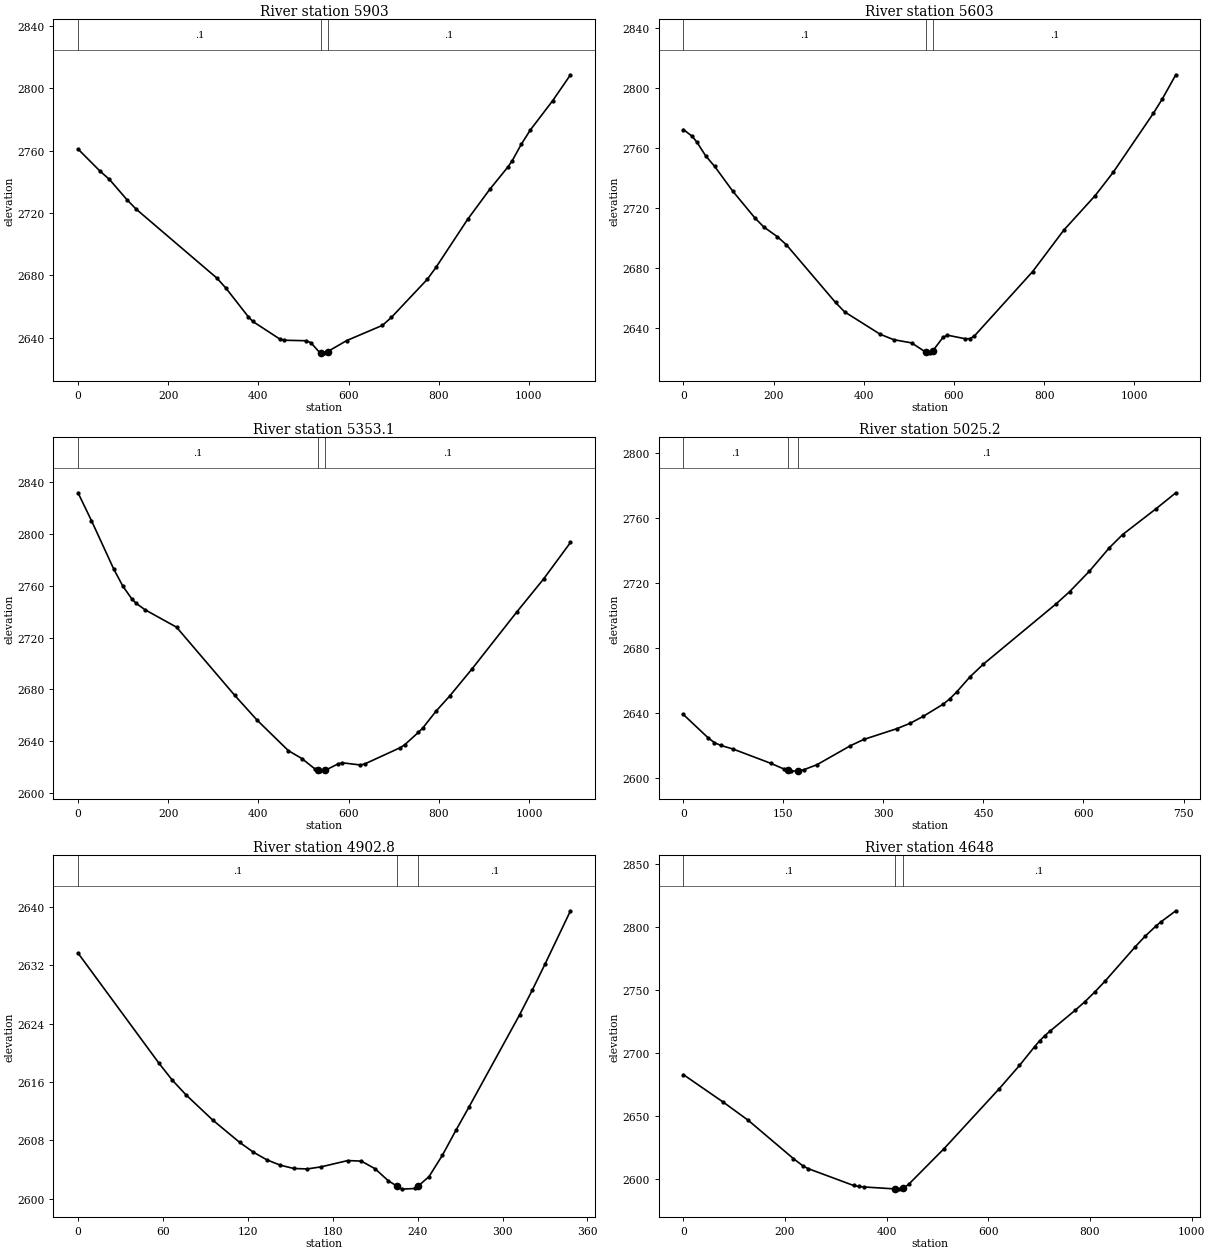
Type RM Length L Ch R = 1 ,5903,296.4,300,304.1
XS GIS Cut Line= 3
     2024903.601      365614.144     2025418.396      365431.756
     2025929.037      365238.539
#Sta/Elev= 30
       0 2760.94    49.6 2746.54    69.5 2741.49   109.2 2728.21   129.1 2722.34
   307.8 2678.19   327.7 2671.81   377.3 2653.48   387.3 2650.39   446.8 2639.18
   456.8 2638.30   506.4 2637.96   516.4 2636.70   536.2 2630.30   538.6 2630.23
   546.2 2630.02   553.6 2631.01   595.8 2638.07   675.2 2647.85   695.0 2652.96
   774.5 2677.36   794.3 2685.22   863.8 2715.75   913.4 2735.20   953.2 2749.38
   963.1 2753.56   982.9 2763.93  1002.8 2773.07  1052.4 2791.86  1092.1 2808.55
#Mann= 3 , 0 , 0
       0     0.1       0   538.6   0.045       0   553.6     0.1       0
Bank Sta=   538.6,   553.6
Exp/Cntr=0.3,0.1

Type RM Length L Ch R = 1 ,5603,254.1,249.9,245.7
XS GIS Cut Line= 3
     2024943.058      365821.581     2025480.251      365723.908
     2026017.444      365626.235
#Sta/Elev= 30
       0 2772.33    19.8 2767.77    29.8 2764.03    49.6 2754.75    69.5 2747.74
   109.2 2731.43   158.8 2713.38   178.7 2707.34   208.5 2700.96   228.3 2695.63
   337.5 2657.13   357.4 2650.94   436.8 2635.92   466.6 2632.36   506.3 2630.21
   538.5 2623.86   546.0 2623.41   553.5 2625.06   575.8 2633.90   585.7 2635.36
   625.4 2632.97   635.4 2633.03   645.3 2634.80   774.3 2677.61   843.8 2705.36
   913.3 2728.33   953.0 2743.74  1042.4 2783.17  1062.2 2792.74  1092.0 2808.75
#Mann= 3 , 0 , 0
       0     0.1       0   538.5   0.045       0   553.5     0.1       0
Bank Sta=   538.5,   553.5
Exp/Cntr=0.3,0.1

Type RM Length L Ch R = 1 ,5353.1,332.9,327.9,322.9
XS GIS Cut Line= 3
     2025024.867      366161.341     2025534.753      365966.066
     2026044.639      365770.791
#Sta/Elev= 30
       0 2831.42    29.8 2809.98    79.4 2772.55    99.3 2759.63   119.1 2749.83
   129.0 2746.31   148.9 2741.32   218.4 2727.99   347.4 2675.51   397.1 2656.39
   466.6 2632.85   496.4 2626.82   526.2 2618.58   532.6 2617.65   536.1 2617.14
   547.6 2617.66   575.8 2622.58   585.7 2623.57   625.4 2621.90   635.4 2622.60
   714.8 2635.25   724.7 2637.53   754.5 2646.92   764.4 2650.30   794.2 2663.45
   824.0 2674.90   873.6 2695.80   972.9 2739.66  1032.4 2765.10  1092.0 2793.19
#Mann= 3 , 0 , 0
       0     0.1       0   532.6   0.045       0   547.6     0.1       0
Bank Sta=   532.6,   547.6
Exp/Cntr=0.3,0.1

Type RM Length L Ch R = 1 ,5025.2,117.9,122.4,126.9
XS GIS Cut Line= 3
     2025480.917      366301.964     2025601.865      366299.246
     2026116.253      365957.736
#Sta/Elev= 30
       0 2639.32    37.2 2624.94    46.5 2622.04    55.8 2620.34    74.4 2618.07
   130.9 2609.31   150.8 2605.79   157.4 2605.02   160.8 2604.62   170.8 2604.47
   172.4 2604.61   180.7 2605.34   200.6 2608.46   250.4 2620.08   270.4 2623.94
   320.2 2630.60   340.1 2633.90   360.0 2638.24   389.9 2645.73   399.8 2649.04
   409.8 2653.15   429.7 2662.42   449.6 2670.18   559.2 2707.46   579.1 2714.84
   609.0 2727.52   638.8 2741.89   658.7 2750.00   708.5 2765.78   738.4 2775.68
#Mann= 3 , 0 , 0
       0     0.1       0   157.4   0.045       0   172.4     0.1       0
Bank Sta=   157.4,   172.4
Exp/Cntr=0.3,0.1

Type RM Length L Ch R = 1 ,4902.8,239,254.8,270.6
XS GIS Cut Line= 4
     2025500.848      366409.322     2025595.976      366413.398
     2025754.974      366348.168     2025835.153      366337.297
#Sta/Elev= 28
       0 2633.68    57.1 2618.60    66.6 2616.26    76.2 2614.26    95.2 2610.78
   114.3 2607.71   123.9 2606.38   133.4 2605.33   143.0 2604.59   152.5 2604.14
   162.0 2604.08   171.6 2604.36   190.7 2605.23   200.2 2605.15   209.8 2604.12
   219.3 2602.45   225.5 2601.71   228.9 2601.31   238.4 2601.40   240.5 2601.75
   248.0 2603.02   257.5 2605.96   267.1 2609.40   276.1 2612.51   312.0 2625.20
   321.0 2628.60   330.0 2632.17   348.0 2639.48
#Mann= 3 , 0 , 0
       0     0.1       0   225.5   0.045       0   240.5     0.1       0
Bank Sta=   225.5,   240.5
Exp/Cntr=0.3,0.1

Type RM Length L Ch R = 1 ,4648,448.2,441.2,434.1
XS GIS Cut Line= 3
     2025347.739      366474.552     2025778.530      366614.525
     2026294.237      366605.120
#Sta/Elev= 30
       0 2682.64    78.8 2660.69   128.0 2646.25   216.6 2615.95   236.3 2609.88
   246.2 2607.92   334.8 2594.64   344.6 2593.84   354.5 2593.48   416.4 2591.91
   423.4 2591.74   431.4 2592.45   433.3 2592.62   443.1 2595.49   512.5 2623.69
   621.6 2671.48   661.3 2689.88   691.0 2704.78   700.9 2709.40   710.9 2713.43
   720.8 2716.93   770.4 2733.53   790.2 2740.54   810.0 2748.41   829.9 2756.91
   889.4 2784.25   909.2 2792.73   929.1 2800.27   939.0 2803.66   968.8 2812.61
#Mann= 3 , 0 , 0
       0     0.1       0   416.4   0.045       0   431.4     0.1       0
Bank Sta=   416.4,   431.4
Exp/Cntr=0.3,0.1

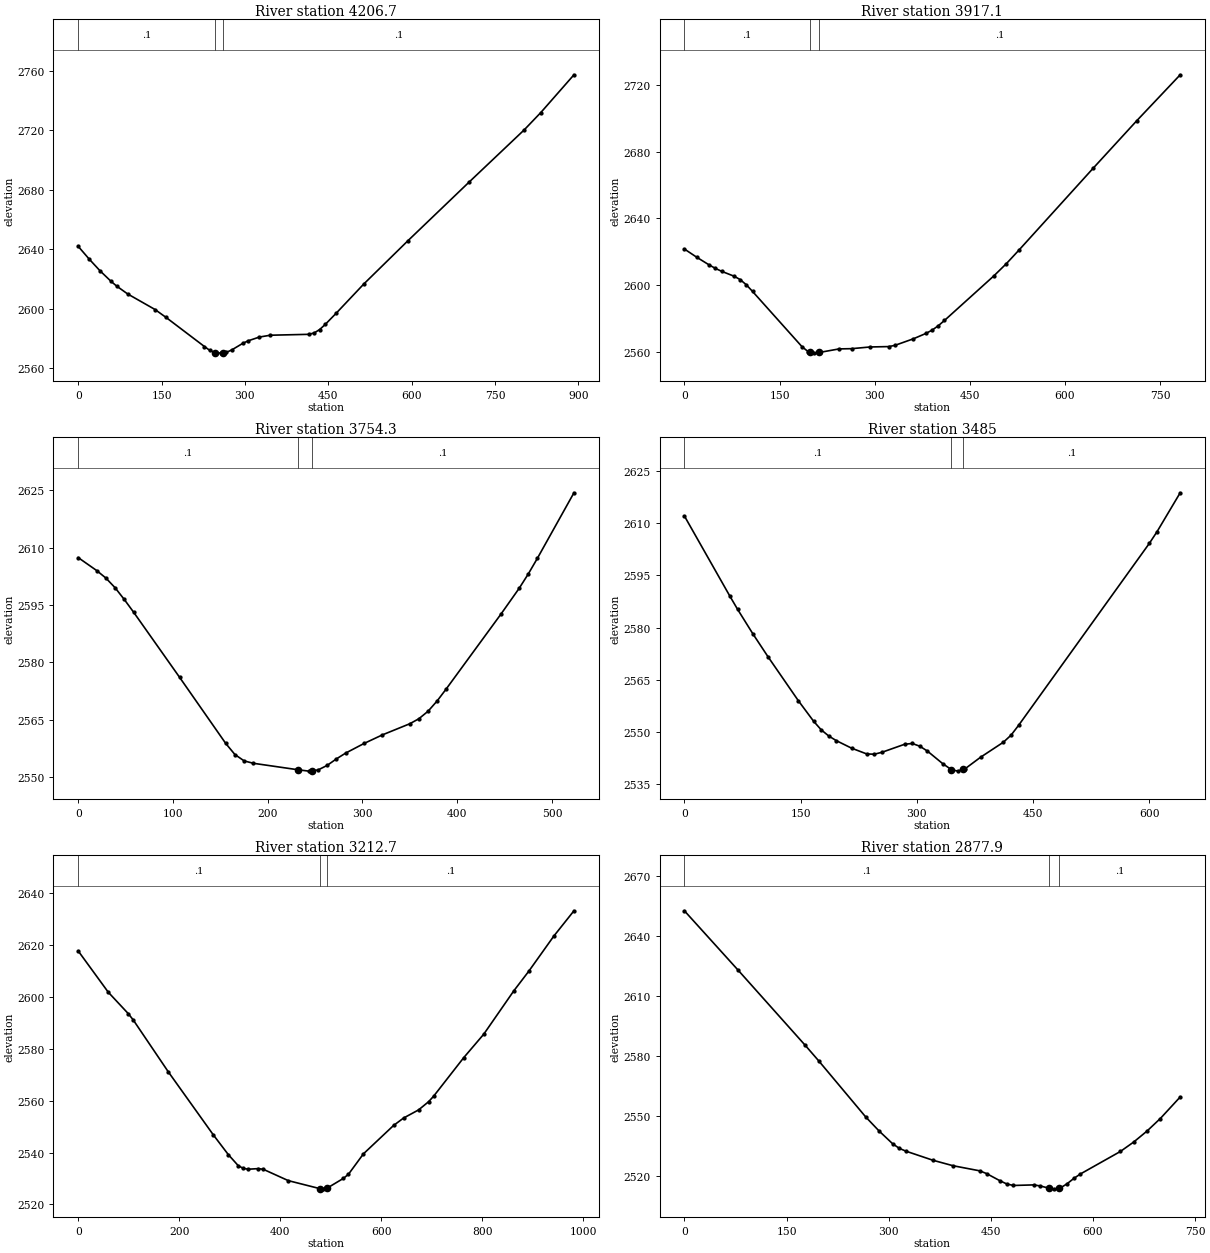
Type RM Length L Ch R = 1 ,4206.7,285.8,289,292.1
XS GIS Cut Line= 3
     2025312.406      366970.573     2025756.786      366973.291
     2026203.712      366998.725
#Sta/Elev= 30
       0 2641.94    19.8 2633.38    39.5 2625.44    59.2 2618.42    69.1 2615.30
    88.9 2610.01   138.2 2599.55   158.0 2594.25   227.1 2574.70   237.0 2572.04
   245.6 2570.66   256.8 2570.26   260.6 2570.45   266.6 2570.76   276.5 2572.45
   296.3 2576.86   306.1 2578.56   325.9 2581.04   345.6 2582.28   414.8 2582.88
   424.6 2583.80   434.5 2586.11   444.4 2589.48   464.3 2597.08   514.0 2616.71
   593.6 2645.83   703.0 2684.95   802.5 2720.13   832.4 2731.77   892.0 2757.10
#Mann= 3 , 0 , 0
       0     0.1       0   245.6   0.045       0   260.6     0.1       0
Bank Sta=   245.6,   260.6
Exp/Cntr=0.3,0.1

Type RM Length L Ch R = 1 ,3917.1,159.4,162.5,165.5
XS GIS Cut Line= 3
     2025332.337      367228.775     2025699.257      367283.134
     2026110.116      367288.570
#Sta/Elev= 30
       0 2621.55    19.5 2616.61    39.0 2612.02    48.8 2609.95    58.6 2608.21
    78.1 2605.29    87.8 2603.26    97.6 2600.11   107.4 2596.14   185.5 2562.96
   195.2 2560.02   197.7 2559.80   205.0 2559.14   212.7 2559.54   244.0 2561.67
   263.6 2561.81   292.8 2562.83   322.1 2563.06   331.9 2563.79   361.2 2567.75
   380.7 2570.93   390.5 2572.90   400.3 2575.54   410.1 2578.72   488.3 2605.56
   507.9 2612.86   527.5 2620.88   644.8 2670.08   713.3 2698.46   781.8 2726.00
#Mann= 3 , 0 , 0
       0     0.1       0   197.7   0.045       0   212.7     0.1       0
Bank Sta=   197.7,   212.7
Exp/Cntr=0.3,0.1

Type RM Length L Ch R = 1 ,3754.3,266,269.6,273.2
XS GIS Cut Line= 3
     2025346.833      367349.723     2025649.660      367422.250
     2025861.426      367422.201
#Sta/Elev= 30
       0 2607.44    19.5 2604.05    29.2 2602.09    38.9 2599.56    48.6 2596.49
    58.4 2593.18   107.0 2576.11   155.7 2558.81   165.4 2555.90   175.2 2554.23
   184.9 2553.61   232.2 2551.91   243.3 2551.56   247.2 2551.68   253.0 2551.85
   262.7 2553.05   272.5 2554.76   282.2 2556.27   301.7 2558.80   321.0 2561.04
   349.9 2563.95   359.5 2565.26   369.2 2567.22   378.8 2569.92   388.4 2573.06
   446.2 2592.66   465.4 2599.40   475.0 2603.15   484.6 2607.24   523.2 2624.39
#Mann= 3 , 0 , 0
       0     0.1       0   232.2   0.045       0   247.2     0.1       0
Bank Sta=   232.2,   247.2
Exp/Cntr=0.3,0.1

Type RM Length L Ch R = 1 ,3485,272.4,272.3,272.1
XS GIS Cut Line= 3
     2025223.620      367519.140     2025605.942      367696.711
     2025823.375      367716.643
#Sta/Elev= 30
       0 2611.97    58.8 2588.94    68.6 2585.22    88.2 2578.24   107.8 2571.64
   147.0 2559.02   166.7 2553.13   176.5 2550.67   186.3 2548.88   196.1 2547.55
   215.7 2545.40   235.3 2543.74   245.1 2543.66   254.9 2544.21   284.3 2546.52
   294.1 2546.74   303.9 2545.95   313.7 2544.55   333.3 2540.97   344.6 2539.24
   352.9 2538.81   359.6 2539.32   362.7 2539.56   382.3 2542.80   411.7 2547.10
   421.6 2549.12   431.5 2551.99   600.2 2604.16   610.1 2607.50   639.9 2618.63
#Mann= 3 , 0 , 0
       0     0.1       0   344.6   0.045       0   359.6     0.1       0
Bank Sta=   344.6,   359.6
Exp/Cntr=0.3,0.1

Type RM Length L Ch R = 1 ,3212.7,361.1,334.7,308.2
XS GIS Cut Line= 3
     2024993.602      367715.220     2025472.027      367931.992
     2025926.656      367891.496
#Sta/Elev= 30
       0 2617.81    59.5 2601.89    99.1 2593.62   109.0 2591.17   178.4 2571.15
   267.6 2546.80   297.3 2539.18   317.1 2534.88   327.0 2533.87   337.0 2533.55
   356.8 2533.78   366.7 2533.50   416.2 2529.13   478.6 2526.05   485.6 2525.86
   493.6 2526.32   525.2 2530.01   535.2 2531.60   564.9 2539.49   624.5 2550.43
   644.3 2553.30   674.1 2556.45   693.9 2559.61   703.8 2561.72   763.4 2576.60
   803.1 2585.67   862.6 2602.40   892.4 2610.01   942.0 2623.58   981.7 2633.30
#Mann= 3 , 0 , 0
       0     0.1       0   478.6   0.045       0   493.6     0.1       0
Bank Sta=   478.6,   493.6
Exp/Cntr=0.3,0.1

Type RM Length L Ch R = 1 ,2877.9,114.7,112.7,110.6
XS GIS Cut Line= 3
     2025181.819      368550.137     2025611.377      368157.852
     2025686.909      368032.425
#Sta/Elev= 30
       0 2652.76    78.9 2622.99   177.5 2585.29   197.2 2577.54   266.2 2549.42
   285.9 2542.36   305.6 2536.03   315.5 2533.67   325.4 2532.24   364.8 2527.71
   394.4 2524.95   433.8 2522.38   443.7 2521.02   463.4 2517.42   473.3 2515.82
   483.1 2515.04   512.7 2515.33   522.6 2514.81   535.8 2513.64   542.3 2513.21
   550.8 2513.73   552.2 2513.81   562.0 2515.89   571.9 2518.57   581.7 2520.83
   640.3 2532.09   659.8 2536.81   679.3 2542.29   698.9 2548.59   728.1 2559.40
#Mann= 3 , 0 , 0
       0     0.1       0   535.8   0.045       0   550.8     0.1       0
Bank Sta=   535.8,   550.8
Exp/Cntr=0.3,0.1

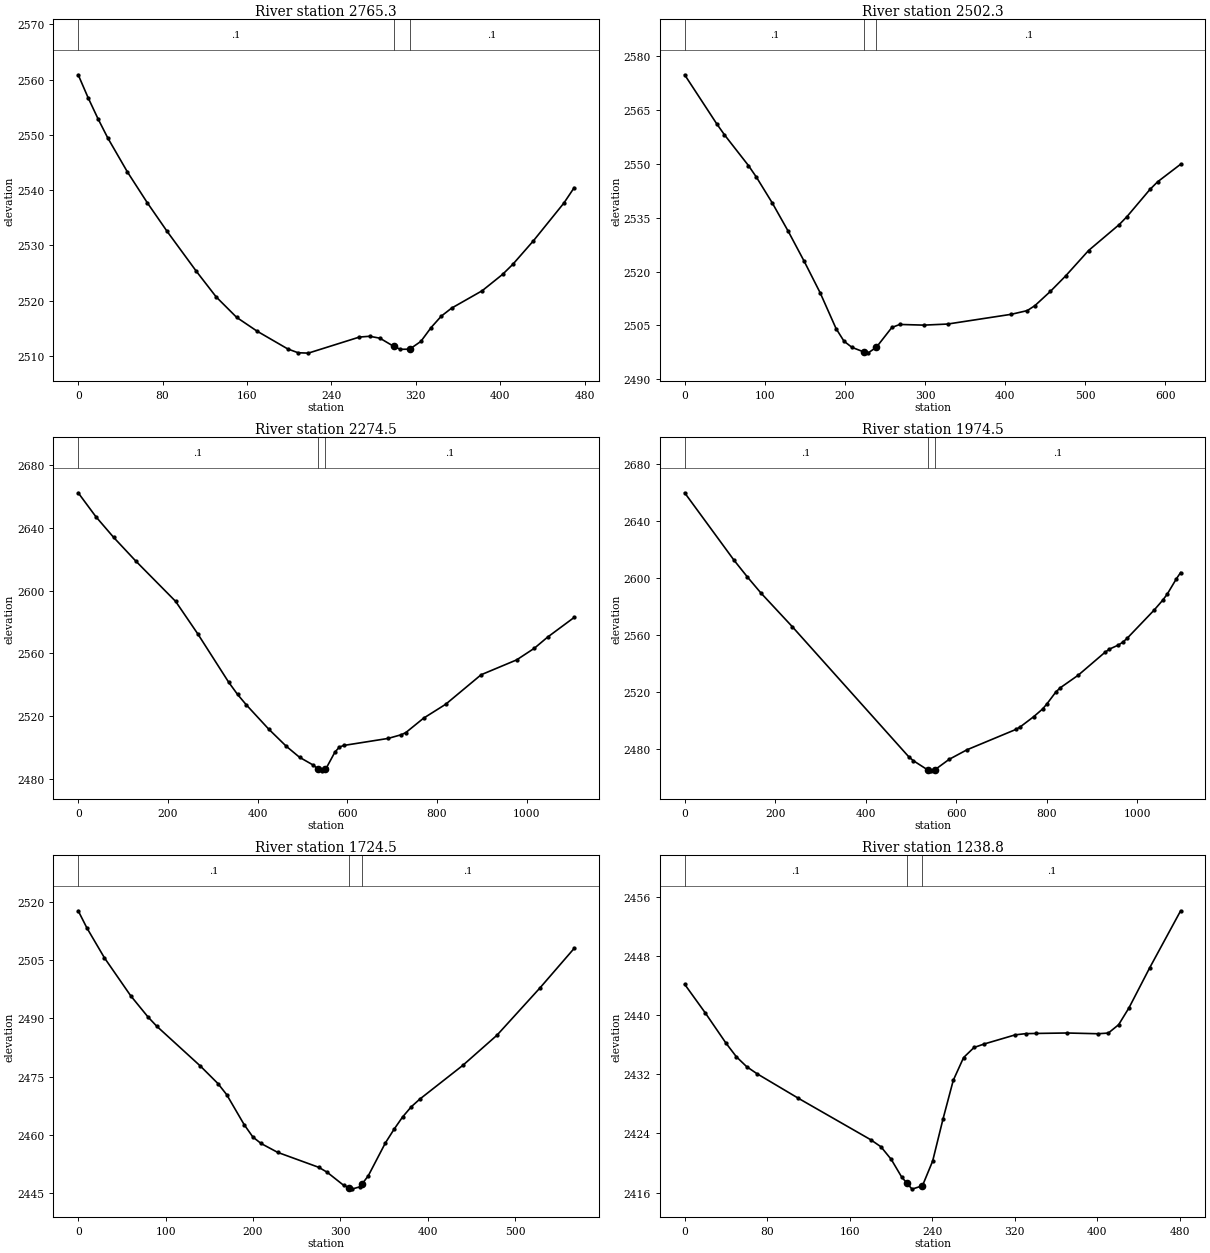
Type RM Length L Ch R = 1 ,2765.3,258.6,263,267.4
XS GIS Cut Line= 4
     2025458.603      368467.293     2025555.090      368378.960
     2025712.729      368207.731     2025754.857      368109.886
#Sta/Elev= 30
       0 2560.86     9.3 2556.75    18.7 2552.93    28.0 2549.44    46.7 2543.26
    65.4 2537.73    84.1 2532.57   112.1 2525.27   130.8 2520.66   150.2 2516.96
   169.6 2514.46   198.7 2511.24   208.4 2510.56   218.1 2510.49   266.6 2513.40
   276.3 2513.54   286.0 2513.19   299.2 2511.70   305.4 2511.18   314.2 2511.21
   324.8 2512.61   334.5 2515.12   344.2 2517.19   353.9 2518.63   382.9 2521.78
   402.3 2524.75   412.0 2526.57   431.4 2530.80   460.4 2537.66   470.1 2540.43
#Mann= 3 , 0 , 0
       0     0.1       0   299.2   0.045       0   314.2     0.1       0
Bank Sta=   299.2,   314.2
Exp/Cntr=0.3,0.1

Type RM Length L Ch R = 1 ,2502.3,237.8,227.8,219.7
XS GIS Cut Line= 3
     2025576.950      368621.711     2025921.221      368368.038
     2026024.502      368206.775
#Sta/Elev= 30
       0 2574.81    39.8 2561.23    49.7 2558.09    79.6 2549.54    89.5 2546.32
   109.4 2539.10   129.3 2531.21   149.2 2522.86   169.1 2514.10   189.0 2504.11
   198.9 2500.60   208.8 2498.89   224.4 2497.54   228.7 2497.28   239.4 2498.94
   258.6 2504.42   268.5 2505.27   298.4 2505.08   328.2 2505.38   407.8 2508.10
   427.6 2509.12   437.2 2510.51   456.4 2514.45   475.5 2518.77   504.2 2525.87
   542.5 2533.10   552.1 2535.30   580.8 2542.88   590.4 2545.01   619.1 2549.90
#Mann= 3 , 0 , 0
       0     0.1       0   224.4   0.045       0   239.4     0.1       0
Bank Sta=   224.4,   239.4
Exp/Cntr=0.3,0.1

Type RM Length L Ch R = 1 ,2274.5,297.1,300,299.8
XS GIS Cut Line= 3
     2025703.386      369074.263     2025960.811      368596.186
     2026271.339      368126.421
#Sta/Elev= 30
       0 2662.49    39.5 2647.21    79.0 2634.04   128.3 2618.94   217.2 2593.17
   266.6 2572.42   335.7 2541.45   355.4 2533.70   375.2 2526.96   424.5 2511.66
   464.0 2500.61   493.6 2493.56   523.2 2488.73   535.5 2485.98   543.0 2484.71
   550.5 2486.04   552.9 2486.46   572.6 2496.89   582.5 2500.08   592.4 2501.12
   691.2 2505.60   720.8 2507.99   730.7 2509.34   770.2 2518.52   819.6 2527.43
   898.6 2546.27   977.7 2555.75  1017.2 2563.17  1046.8 2570.30  1106.1 2582.88
#Mann= 3 , 0 , 0
       0     0.1       0   535.5   0.045       0   550.5     0.1       0
Bank Sta=   535.5,   550.5
Exp/Cntr=0.3,0.1

Type RM Length L Ch R = 1 ,1974.5,253.8,249.9,246.4
XS GIS Cut Line= 3
     2025903.406      369180.607     2026220.855      368737.608
     2026518.436      368273.885
#Sta/Elev= 30
       0 2660.04   109.0 2612.67   138.7 2600.83   168.4 2589.64   237.8 2565.92
   495.4 2474.37   505.4 2471.67   537.5 2465.12   545.0 2464.35   552.5 2465.19
   584.4 2472.62   623.7 2479.33   731.9 2493.66   741.8 2495.52   771.3 2502.63
   791.0 2508.05   800.8 2511.74   820.5 2520.09   830.3 2523.01   869.7 2531.80
   928.7 2547.86   938.6 2550.13   958.2 2552.97   968.1 2554.97   977.9 2557.78
  1037.0 2577.43  1056.6 2584.60  1066.5 2588.85  1086.2 2599.37  1096.0 2603.99
#Mann= 3 , 0 , 0
       0     0.1       0   537.5   0.045       0   552.5     0.1       0
Bank Sta=   537.5,   552.5
Exp/Cntr=0.3,0.1

Type RM Length L Ch R = 1 ,1724.5,466,485.7,506.2
XS GIS Cut Line= 4
     2026232.876      369047.519     2026400.209      368938.234
     2026457.557      368819.213     2026539.095      368598.155
#Sta/Elev= 30
       0 2517.74    10.0 2513.30    30.0 2505.63    60.0 2495.87    79.9 2490.38
    89.9 2488.00   139.9 2477.72   159.9 2473.23   169.9 2470.38   189.9 2462.65
   199.9 2459.45   209.3 2457.78   228.2 2455.50   275.4 2451.63   284.8 2450.39
   303.7 2447.02   310.3 2446.32   313.1 2446.02   322.5 2446.63   325.3 2447.47
   332.0 2449.47   351.6 2457.94   361.4 2461.42   371.2 2464.60   381.1 2467.22
   390.9 2469.21   440.0 2477.88   479.2 2485.67   528.3 2497.83   567.6 2508.06
#Mann= 3 , 0 , 0
       0     0.1       0   310.3   0.045       0   325.3     0.1       0
Bank Sta=   310.3,   325.3
Exp/Cntr=0.3,0.1

Type RM Length L Ch R = 1 ,1238.8,177.8,172.1,166.5
XS GIS Cut Line= 2
     2026604.325      369134.492     2027069.996      369014.904
#Sta/Elev= 30
       0 2444.14    20.0 2440.27    40.1 2436.18    50.1 2434.35    60.1 2433.01
    70.1 2432.06   110.2 2428.74   180.3 2423.14   190.3 2422.18   200.3 2420.47
   210.3 2418.11   215.5 2417.26   220.4 2416.46   230.5 2416.91   240.4 2420.25
   250.4 2425.91   260.4 2431.17   270.4 2434.24   280.5 2435.60   290.5 2436.08
   320.5 2437.31   330.5 2437.47   340.6 2437.50   370.6 2437.56   400.6 2437.46
   410.7 2437.55   420.7 2438.68   430.7 2440.95   450.7 2446.34   480.8 2454.07
#Mann= 3 , 0 , 0
       0     0.1       0   215.5   0.045       0   230.5     0.1       0
Bank Sta=   215.5,   230.5
Exp/Cntr=0.3,0.1

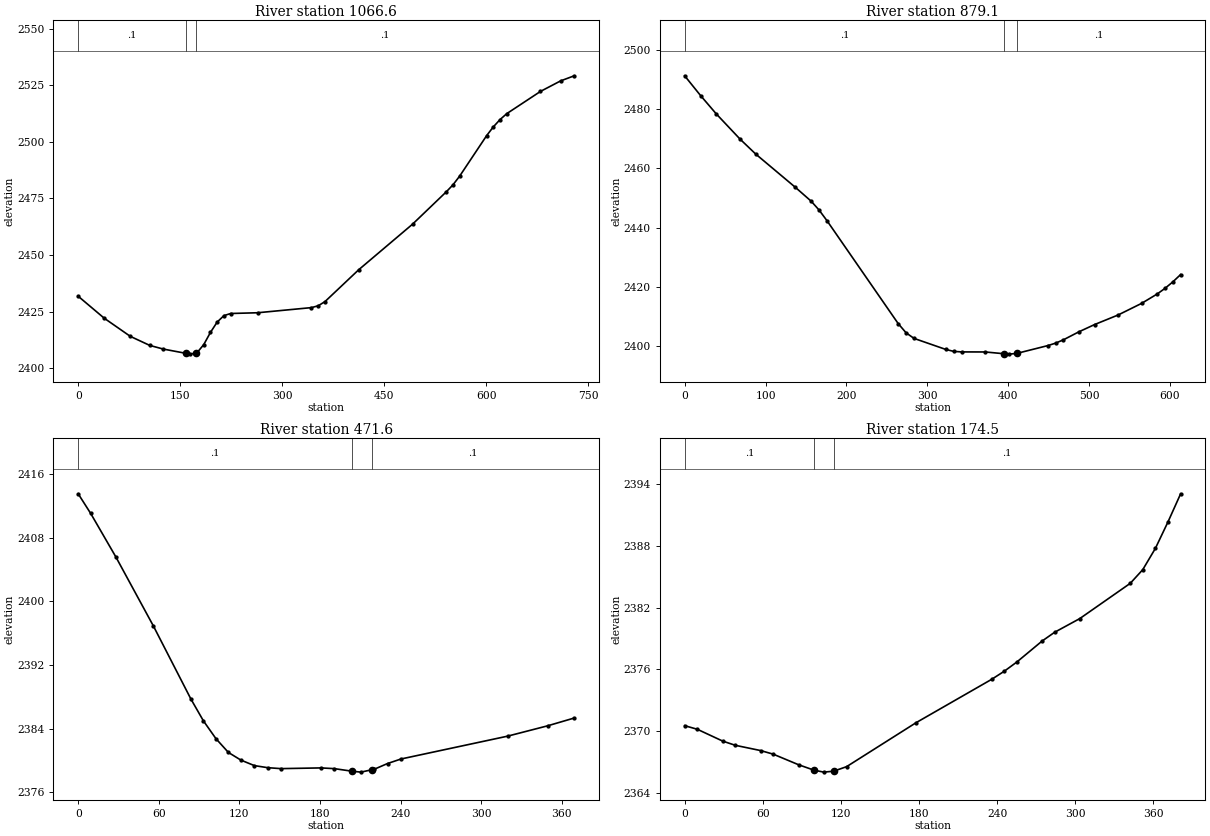
Type RM Length L Ch R = 1 ,1066.6,186.4,187.6,188.7
XS GIS Cut Line= 3
     2026713.042      369263.141     2026818.135      369270.388
     2027365.017      368969.951
#Sta/Elev= 30
       0 2431.82    38.3 2422.12    76.6 2414.12   105.3 2410.11   125.2 2408.50
   158.6 2406.61   164.8 2406.27   173.6 2406.82   174.7 2406.89   184.6 2410.47
   194.5 2415.88   204.4 2420.45   214.3 2423.27   224.2 2424.21   263.8 2424.54
   343.0 2426.81   353.0 2427.63   362.9 2429.47   412.4 2443.51   491.6 2463.64
   541.1 2477.89   551.0 2480.99   560.9 2484.86   600.6 2502.75   610.5 2506.64
   620.4 2509.87   630.3 2512.48   679.8 2522.28   709.5 2526.94   729.3 2529.16
#Mann= 3 , 0 , 0
       0     0.1       0   158.6   0.045       0   173.6     0.1       0
Bank Sta=   158.6,   173.6
Exp/Cntr=0.3,0.1

Type RM Length L Ch R = 1 ,879.1,425.4,407.3,389.3
XS GIS Cut Line= 3
     2026607.949      369553.052     2026957.655      369400.849
     2027166.029      369299.380
#Sta/Elev= 30
       0 2491.30    19.6 2484.65    39.1 2478.43    68.5 2469.91    88.0 2464.83
   136.9 2453.62   156.5 2448.92   166.2 2445.95   176.0 2442.34   264.0 2407.59
   273.8 2404.47   283.6 2402.59   322.7 2398.88   332.5 2398.21   342.3 2398.03
   371.6 2398.01   395.3 2397.40   400.7 2397.28   410.3 2397.50   449.0 2400.16
   458.6 2400.99   468.3 2402.12   487.6 2404.84   506.9 2407.28   535.9 2410.50
   564.9 2414.42   584.2 2417.59   593.8 2419.48   603.5 2421.67   613.2 2424.16
#Mann= 3 , 0 , 0
       0     0.1       0   395.3   0.045       0   410.3     0.1       0
Bank Sta=   395.3,   410.3
Exp/Cntr=0.3,0.1

Type RM Length L Ch R = 1 ,471.6,292.4,297,295.4
XS GIS Cut Line= 3
     2026983.358      369905.074     2027071.690      369822.177
     2027150.510      369587.077
#Sta/Elev= 23
       0 2413.53     9.3 2411.06    28.0 2405.60    55.9 2396.93    83.9 2387.72
    93.2 2384.98   102.5 2382.75   111.8 2381.01   121.1 2380.05   131.1 2379.36
   141.0 2379.10   150.9 2378.98   180.6 2379.07   190.6 2378.98   203.6 2378.66
   210.4 2378.54   218.6 2378.84   220.3 2378.90   230.2 2379.62   240.2 2380.19
   319.5 2383.06   349.3 2384.36   369.1 2385.34
#Mann= 3 , 0 , 0
       0     0.1       0   203.6   0.045       0   218.6     0.1       0
Bank Sta=   203.6,   218.6
Exp/Cntr=0.3,0.1

Type RM Length L Ch R = 1 ,174.5,179.1,174.5,176
XS GIS Cut Line= 4
     2027340.765      369811.305     2027387.622      369715.176
     2027402.007      369655.747     2027333.970      369453.899
#Sta/Elev= 23
       0 2370.53     9.7 2370.18    29.2 2369.03    38.9 2368.62    58.3 2368.11
    68.0 2367.76    87.5 2366.73    99.4 2366.20   106.9 2366.01   114.4 2366.10
   124.4 2366.54   177.8 2370.82   235.9 2375.04   245.5 2375.82   255.2 2376.72
   274.6 2378.76   284.3 2379.62   303.6 2380.95   342.4 2384.38   352.0 2385.71
   361.7 2387.78   371.4 2390.36   381.1 2393.09
#Mann= 3 , 0 , 0
       0     0.1       0    99.4   0.045       0   114.4     0.1       0
Bank Sta=    99.4,   114.4
Exp/Cntr=0.3,0.1